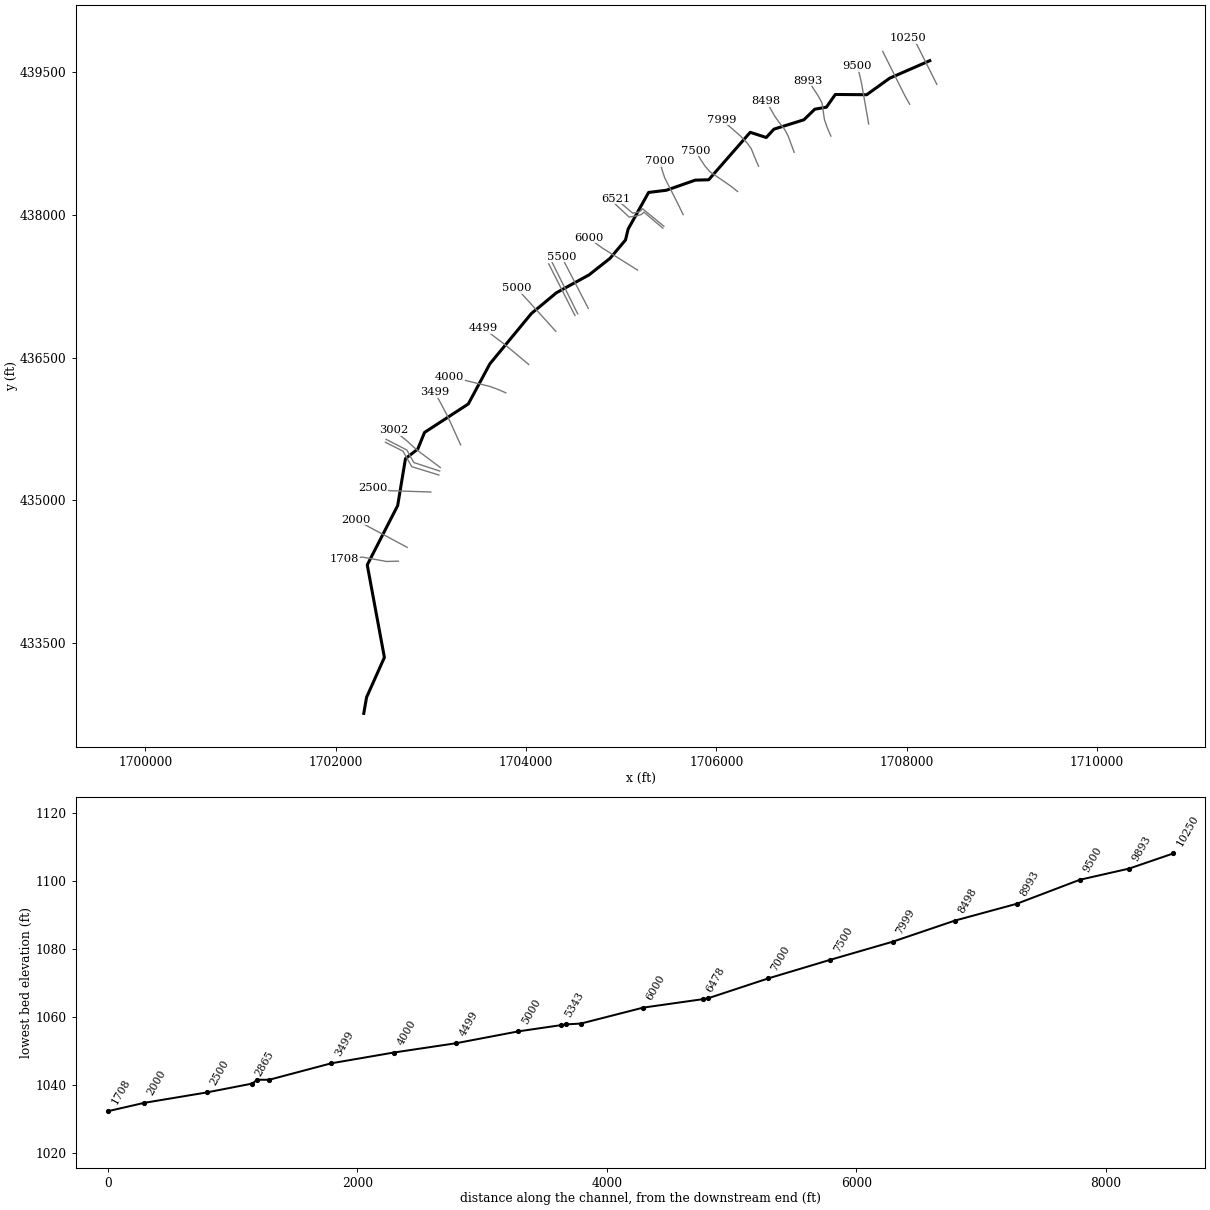
--- CAPPORN.prj (project) ---

Proj Title=CAPPORN
Current Plan=p01
Default Exp/Contr=0,0
English Units
Geom File=g01
Flow File=f01
Plan File=p01
BEGIN DESCRIPTION:
---------- MODELED AS PART OF WVEMD CTP PROGRAM, 2023----------
Stream Name: Cappo Run
Flood Zone:  AFH
Wetzel County, WV
HEC-RAS Version: RAS 6.3
Vertical Datum: NAVD88
Projection: NAD 1983 StatePlane West Virginia S FIPS 4702 (US Feet)
Terrain: 1-meter West Virginia FEMA R3 South Central (collected 2018-2020)
Land Use: 2019 NLCD
Hydrologic Method:
WV SIR2010-5033 regression equations
Additional Model Notes:
None
END DESCRIPTION:
DSS Export Rating Curves= 0
DSS Export Rating Curve Sorted= 0
DSS Export Volume Flow Curves= 0
DXF OffsetX= 0
DXF OffsetY= 0
DXF ScaleX= 0
DXF ScaleY= 0

--- CAPPORN.p01 (plan) ---

Plan Title=Floodplain
Program Version=6.30
Short Identifier=Floodplain
Geom File=g01
Flow File=f01
Subcritical Flow
K Sum by GR= 0
Std Step Tol= 0.01
Critical Tol= 0.01
Num of Std Step Trials= 20
Max Error Tol= 0.3
Flow Tol Ratio= 0.001
Split Flow NTrial= 30
Split Flow Tol= 0.02
Split Flow Ratio= 0.02
Log Output Level= 0
Friction Slope Method= 1
Unsteady Friction Slope Method= 2
Unsteady Bridges Friction Slope Method= 1
Parabolic Critical Depth
Global Vel Dist= 0 , 0 , 0
Global Log Level= 0
CheckData=True
Encroach Param=-1 ,0,0, 0
Mapping Interval=1HOUR
Computation Time Step Use Courant=        0
Computation Time Step Use Time Series=    0
Computation Time Step Count To Double=0
Computation Time Step Max Doubling=0
Computation Time Step Max Halving=0
Computation Time Step Residence Courant=0
Run HTab= 0
Run UNet= 0
Run Sediment= 0
Run PostProcess= 0
Run WQNet= 0
Run RASMapper= 0
UNET Theta= 0
UNET Theta Warmup= 0
UNET ZTol= 0
UNET ZSATol= 0
UNET MxIter= 0
UNET Max Iter WO Improvement= 0
UNET MaxInSteps= 0
UNET DtIC= 0
UNET DtMin= 0
UNET MaxCRTS= 0
UNET WFStab= 0
UNET SFStab= 0
UNET WFX= 1
UNET SFX= 1
UNET Gravity=32.17405
UNET 1D Methodology=Finite Difference
UNET DSS MLevel= 1
UNET Pardiso=0
UNET DZMax Abort= 0
UNET Use Existing IB Tables= 0
UNET Froude Reduction=False
UNET Froude Limit= 0
UNET Froude Power= 0
UNET D1 Cores= 0
UNET WindReference=Eulerian
UNET WindDragFormulation=Hsu (1988)
UNET D2 Coriolis=0
UNET D2 Cores= 0
UNET D2 Theta= 1
UNET D2 Theta Warmup= 1
UNET D2 Z Tol= 0.01
UNET D2 Volume Tol= 0.01
UNET D2 Max Iterations= 20
UNET D2 Equation= 0
UNET D2 RampUpFraction=0.1
UNET D2 TimeSlices= 1
UNET D2 Turbulence Formulation=Non-Conservative (original)
UNET D2 Eddy Viscosity=0.3
UNET D2 Transverse Eddy Viscosity=0.1
UNET D2 Smagorinsky Mixing=0
UNET D2 BCVolumeCheck=0
UNET D2 Cores=0
UNET D2 SolverType=PARDISO (Direct)
UNET D2 Minimum Iterations= 3
UNET D2 Maximum Iterations= 30
UNET D2 Restart Number= 10
UNET D2 Relaxation Coeff=1.3
UNET D2 SOR Precondition Iterations= 10
UNET D2 ILUT Maximum Fill= 8
UNET D2 ILUT Tolerance=1E-08
UNET D2 Convergence Tolerance=0.00001
UNET D1D2 MaxIter= 0
UNET D1D2 ZTol=0.01
UNET D1D2 QTol=0.1
UNET D1D2 MinQTol=1
Write IC File= 0
Write IC File at Fixed DateTime=0
Write IC File at Sim End=0
Echo Input=False
Echo Parameters=False
Echo Output=False
Write Detailed= 0
HDF Write Warmup=0
HDF Write Time Slices=0
HDF Flush=0
HDF Compression= 1
HDF Chunk Size= 1
HDF Spatial Parts= 1
HDF Use Max Rows=0
HDF Fixed Rows= 1
Calibration Method= 0
Calibration Iterations= 20
Calibration Max Change=0.05
Calibration Tolerance=0.2
Calibration Maximum=1.5
Calibration Minimum=0.5
Calibration Optimization Method= 1
WQ AD Non Conservative
WQ ULTIMATE=-1
WQ Max Comp Step=1HOUR
WQ Output Interval=15MIN
WQ Output Selected Increments= 0
WQ Output face flow=0
WQ Output face velocity=0
WQ Output face area=0
WQ Output face dispersion=0
WQ Output cell volume=0
WQ Output cell surface area=0
WQ Output cell continuity=0
WQ Output cumulative cell continuity=0
WQ Output face conc=0
WQ Output face dconc_dx=0
WQ Output face courant=0
WQ Output face peclet=0
WQ Output face adv mass=0
WQ Output face disp mass=0
WQ Output cell mass=0
WQ Output cell source sink temp=0
WQ Output nsm pathways=0
WQ Output nsm derived pathways=0
WQ Create Restart=0
WQ Fixed Restart=0
WQ System Summary=0
WQ Write To DSS=0
Sorting and Armoring Iterations= 10
XS Update Threshold= 0.02
Bed Roughness Predictor= 0
Hydraulics Update Threshold= 0.02
Energy Slope Method= 1
Volume Change Method= 1
Sediment Retention Method= 0
Sediment TS Multiplier= 1
Warm Up Method= 0
XS Weighting Method= 0
Number of US Weighted Cross Sections= 1
Number of DS Weighted Cross Sections= 1
Upstream XS Weight=0
Main XS Weight=1
Downstream XS Weight=0
Number of DS XS's Weighted with US Boundary= 1
Upstream Boundary Weight= 1
Weight of XSs Associated with US Boundary= 0
Number of US XS's Weighted with DS Boundary= 1
Downstream Boundary Weight= 0.5
Weight of XSs Associated with DS Boundary= 0.5
Percentile Method= 0
Sediment Output Level= 3
Mass or Volume Output= 0
Output Increment Type= 1
Profile and TS Output Increment= 1
Transport Output Increment 1
XS Output Flag= 0
XS Output Increment= 10
Read HDF5 Sediment Hotstart= 0
Sediment Hotstart Type= 0
Write Gradation File= 0
Read Gradation Hotstart= 0
Write HDF5 File= 1
Write Binary Output= 1
Write DSS Sediment File= 0
DSS Sediment Output Type= 1
SV Curve= 0
Specific Gage Flag= 0
Subcell Erosion Methods= 0
Subcell Deposition Methods= 0
Advection Scheme= 1
Matrix Solver= 0
Implicit Weighting Factor= 1
Maximum Outer Loop Convergence Iterations= 5
Convergence Maximum Absolute= 0.001
Convergence RMSE= 0.0001
Grain Fractions Max Abs Error= 0.001
Max Subgrid Regions= 1
Max Subgrid Length Scale= 3.402823E+38
Initial Layer Thickness= 3.402823E+38
Min Layer Thickness= 3.402823E+38
Max Layer Thickness= 3.402823E+38
Number of Layers= 5

--- CAPPORN.f01 (steady flow) ---

Flow Title=Flow
Program Version=4.00
Number of Profiles=1
Profile Names=F01pct
River Rch & RM=CAPPORN,Main,10250
     708
River Rch & RM=CAPPORN,Main,8993
     796
River Rch & RM=CAPPORN,Main,6521
    1260
River Rch & RM=CAPPORN,Main,5000
    1450
Boundary for River Rch & Prof#=CAPPORN,Main      ,1
Up Type=0
Dn Type=3
Dn Slope=0.005511

--- CAPPORN.g01 (geometry) ---

Geom Title=Geometry
Program Version=6.31

River Reach=CAPPORN         ,Main
Reach XY= 30
     1708242.378      439622.456     1707820.349      439438.044
     1707579.115       439264.48     1707249.549      439267.063
     1707155.535      439133.274     1707034.144      439112.611
     1706919.467      439001.034     1706604.365      438902.371
     1706523.782      438814.556     1706355.383      438869.311
     1705918.889      438370.314     1705777.352      438366.181
     1705473.614       438259.77     1705287.652      438237.041
     1705072.247       437851.17     1705044.869       437737.01
     1704882.669      437544.334     1704662.097      437370.253
     1704319.101      437182.224     1704055.139      436963.203
     1703619.679      436434.761     1703392.908      436012.732
     1702933.169      435713.643     1702861.884      435538.529
     1702732.744        435437.8       1702650.9      434944.298
     1702331.211      434320.789     1702511.387      433347.837
     1702323.938      432928.307     1702294.561      432759.445

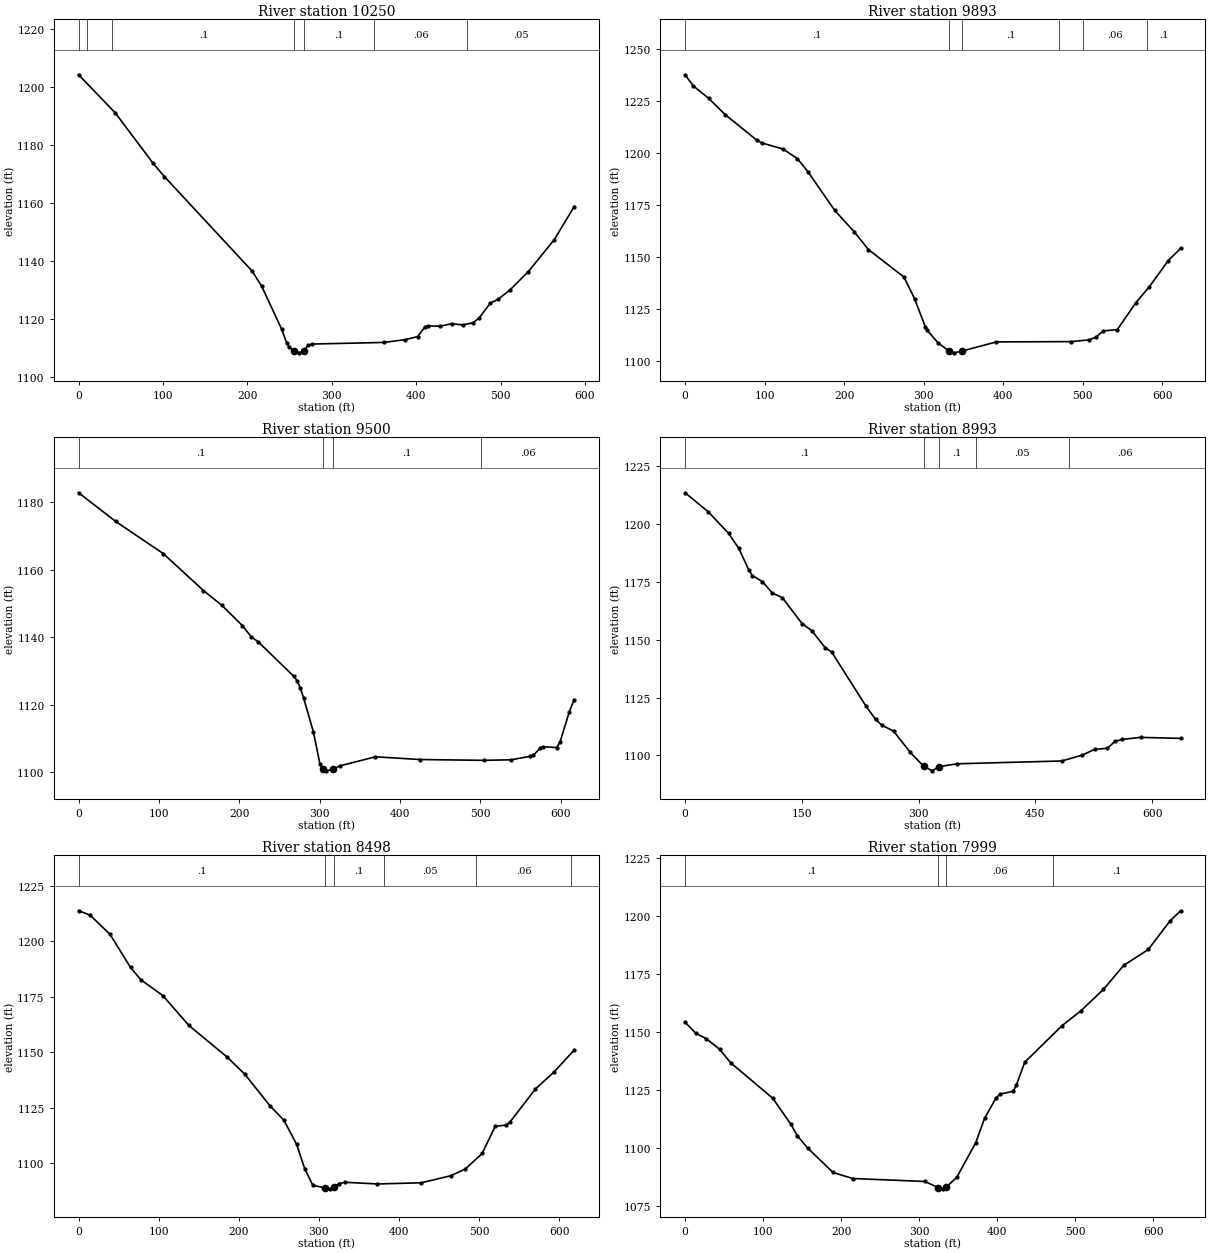
Type RM Length L Ch R = 1 ,10250   ,356.7,357.3,356.8
XS GIS Cut Line= 3
1708316.22603782 439373.663009161708103.60663654439797.572940471
1708007.92790596439857.372147083
#Sta/Elev= 30
       0 1204.21    43.5 1191.02    88.2 1173.67   101.7 1169.04   205.5 1136.46
   216.8 1131.26   240.4 1116.45   246.6 1111.61   249.3 1110.15  255.45 1108.87
   261.5 1108.22   266.6 1108.87   271.7 1110.77   276.2 1111.25   361.2 1111.81
   386.7 1112.76   401.6 1113.82   410.4 1117.21   413.5 1117.52   428.4 1117.41
   441.8 1118.29   455.2 1117.87   467.1 1118.58   474.2 1120.15   487.8 1125.39
   497.2 1126.75   511.4 1130.03   532.7 1136.23   563.3  1147.2   587.1  1158.7
#Mann= 7 ,-1,0
       0      .1       0      10     .05       0      40      .1       0
  255.45    .045       0   266.6      .1       0     350     .06       0
     460     .05       0
Bank Sta=255.45,266.6
XS Rating Curve= 0 ,0
Exp/Cntr(USF)=0,0
Exp/Cntr=0.3,0.1

Type RM Length L Ch R = 1 ,9893    ,392.5,392.8,389.1
XS GIS Cut Line= 3
1708030.57878427  439164.70618511707981.21048001439252.296233011
1707747.83107089439719.770399012
#Sta/Elev= 30
       0 1237.53    10.5 1232.11    29.5 1226.25    50.3  1218.4    89.8 1206.17
    96.2 1204.77   123.2 1201.78   141.1 1197.23   154.5 1190.84     188 1172.32
   212.6 1161.97   230.5 1153.43   275.2 1140.18   288.6  1129.7     302 1116.26
   304.3 1114.67   317.9 1108.55  331.82 1104.59   337.8 1103.73  348.061104.574
   391.4 1108.99   485.3 1109.13   507.7 1109.97   516.6 1111.29   525.5 1114.28
   543.4 1114.89   566.7 1127.87   583.7 1135.54   607.5 1148.15     623 1154.02
#Mann= 6 ,-1,0
       0      .1       0  331.82    .045       0  348.06      .1       0
  470.54     .05       0  500.54     .06       0  580.54      .1       0
Bank Sta=331.82,348.06
XS Rating Curve= 0 ,0
Exp/Cntr(USF)=0,0
Exp/Cntr=0.3,0.1

Type RM Length L Ch R = 1 ,9500    ,507,507.1,504.3
XS GIS Cut Line= 6
1707600.05087492438956.7099829171707583.89145842439049.056911096
1707568.80848335439135.2470274271707525.71244092439381.504737005
1707506.11077408439467.5964283351707481.60885459439561.609035596
#Sta/Elev= 30
       0 1182.83      46 1174.36   105.4  1164.8   155.3 1153.88   178.5 1149.44
   203.7 1143.49     215 1140.13   223.2 1138.75   267.8 1128.45   271.9 1127.16
     276 1124.99     280 1122.03   292.2 1111.97   300.3 1102.51  303.56 1100.89
   308.4 1100.46   316.6 1100.89   324.7 1101.91   369.4 1104.62   424.9 1103.81
   504.1 1103.57   538.3 1103.73   561.9 1104.77     566 1105.08   574.3 1107.21
   578.4  1107.6   594.9 1107.36   599.1 1108.96   610.5 1117.84   616.7 1121.56
#Mann= 4 ,-1,0
       0      .1       0  303.56    .045       0   316.6      .1       0
  501.25     .06       0
Bank Sta=303.56,316.6
XS Rating Curve= 0 ,0
Exp/Cntr(USF)=0,0
Exp/Cntr=0.3,0.1

Type RM Length L Ch R = 1 ,8993    ,490.7,494.6,498.4
XS GIS Cut Line= 6
1707203.06905735438829.3250670881707164.42576192438918.153629586
1707135.02457401439003.6390229171707109.41931026439177.704291582
1707072.32752092439247.9193742571706966.30378284439410.325545505
#Sta/Elev= 30
       0 1213.44    29.7 1205.25    55.8 1195.93    68.9 1189.46      82 1179.99
    86.4 1177.72    99.4 1175.07   112.1 1170.12   124.8  1168.2   150.2 1156.98
   162.8 1153.89   179.8 1146.61   188.2 1144.68   232.7 1121.16   244.8 1115.54
   252.9 1113.07   267.8 1110.52   289.3 1101.33   306.7 1095.27   317.6 1093.37
   325.7 1095.17   349.9 1096.42   483.9 1097.63     510 1100.15     526 1102.62
   542.6 1103.12   552.2 1106.08   561.9 1106.96   585.1 1107.82   636.6 1107.39
#Mann= 5 ,-1,0
       0      .1       0   306.7    .045       0   325.7      .1       0
  373.21     .05       0  492.62     .06       0
Bank Sta=306.7,325.7
XS Rating Curve= 0 ,0
Exp/Cntr(USF)=0,0
Exp/Cntr=0.3,0.1

Type RM Length L Ch R = 1 ,8498    ,499.3,499,497.8
XS GIS Cut Line= 6
1706816.83754633438659.2368245871706752.84751683438833.097697333
1706716.84955734438899.770792335 1706655.3975805438978.731592417
1706612.16735201439040.2370468381706522.55204567439199.061532333
#Sta/Elev= 30
       0 1213.65    14.1 1211.73    39.3 1203.01    64.8 1188.11    77.5 1182.64
   105.2 1175.44   137.4  1162.1   185.3 1147.79   207.4 1140.09   238.6 1125.95
   256.3 1119.31   272.2 1108.45   282.3 1097.46   292.5 1089.96     307 1088.97
   314.4 1088.43  318.371089.043   324.9 1090.81     333 1091.38   373.1 1090.62
   427.9 1091.16   464.5 1094.32     483 1097.41   503.8 1104.36   520.1  1116.6
   533.9 1117.16   538.4 1118.44   570.3 1133.39   593.1 1140.88   618.7 1150.93
#Mann= 6 ,-1,0
       0      .1       0     307    .045       0  318.37      .1       0
  381.13     .05       0  496.31     .06       0  614.35     .05       0
Bank Sta=307,318.37
XS Rating Curve= 0 ,0
Exp/Cntr(USF)=0,0
Exp/Cntr=0.3,0.1

Type RM Length L Ch R = 1 ,7999    ,498.3,499.3,499.1
XS GIS Cut Line= 6
1706443.09321509438511.8132349251706400.94631776438609.925899595
1706366.42210859438696.574676424  1706322.167932438757.833740249
1706253.00960575438830.0767060071706057.86399867439000.725970998
#Sta/Elev= 30
       0 1154.02    13.8 1149.25    26.9 1147.02    44.3 1142.36    58.2 1136.63
   112.5 1121.21   135.4 1110.12     144 1105.04     157  1099.8   189.5 1089.27
   214.8 1086.66   307.1 1085.39   324.3 1082.77   329.9 1082.21  333.961082.798
     348 1087.12   372.4 1102.12   383.7 1112.63   398.1 1121.22   403.5 1123.08
   420.5 1124.27   424.6 1127.09   435.2 1136.82   482.9 1152.55   507.2    1159
     536  1168.2   561.9 1178.54   593.5 1185.42   621.2  1197.7   634.9  1202.1
#Mann= 4 ,-1,0
       0      .1       0   324.3    .045       0  333.96     .06       0
  471.45      .1       0
Bank Sta=324.3,333.96
XS Rating Curve= 0 ,0
Exp/Cntr(USF)=0,0
Exp/Cntr=0.3,0.1

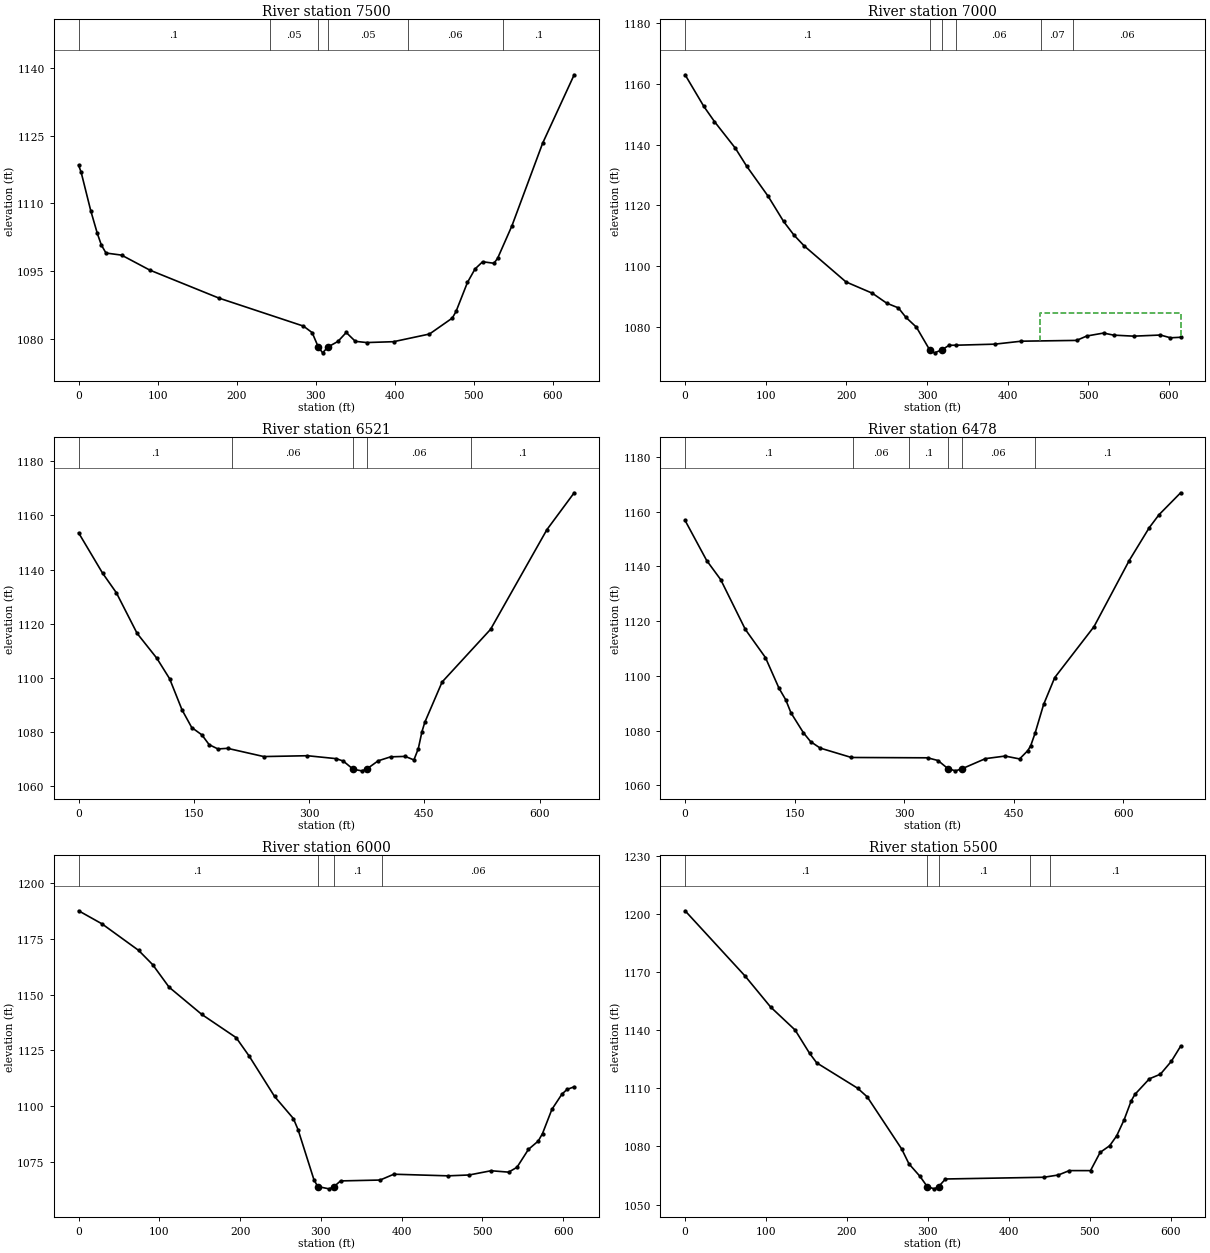
Type RM Length L Ch R = 1 ,7500    ,501.6,500,495.3
XS GIS Cut Line= 6
1706222.62219934438247.0079902561706149.03179534438305.374343336
1705932.67789733 438454.019387261705881.68915418438512.261068672
1705830.60329834438589.203171998 1705780.1004466438676.240071416
#Sta/Elev= 30
       0 1118.47     3.2  1116.9    15.3 1108.41    23.6 1103.38    28.7  1100.8
    34.6 1099.01    54.3 1098.55      90 1095.23   177.2 1089.04   284.3 1082.82
   295.4 1081.37  302.94 1078.26   308.6 1076.89   315.5  1078.2     328 1079.42
   338.5  1081.4     350 1079.44   364.3 1079.17   398.3 1079.36   443.8 1081.06
   472.6 1084.59   477.4 1086.07   491.8 1092.49   501.4 1095.48     511 1097.08
   525.4 1096.74     530 1097.86     548 1105.01   586.9 1123.35   626.8 1138.52
#Mann= 6 ,-1,0
       0      .1       0  241.43     .05       0  302.94    .045       0
   315.5     .05       0  416.42     .06       0  536.19      .1       0
Bank Sta=302.94,315.5
XS Rating Curve= 0 ,0
Exp/Cntr(USF)=0,0
Exp/Cntr=0.3,0.1

Type RM Length L Ch R = 1 ,7000    ,470.4,479.5,489.1
BEGIN DESCRIPTION:
Structure 5 XS 4
END DESCRIPTION:
XS GIS Cut Line= 6
1705650.15024717438003.6590675121705609.81043284438088.334423095
1705570.82264993438166.6771141741705457.36684009438389.451931089
1705429.59032084438473.2066848431705404.48636842438564.659914002
#Sta/Elev= 30
       0 1163.06    23.2 1152.65    36.4 1147.63    62.2 1138.89    76.3 1132.94
     103 1122.99   122.1 1114.71   134.9 1110.23   147.6 1106.65   199.5 1094.76
   232.2 1091.03     250 1087.75   264.4 1086.21   273.8 1083.08   286.8 1079.84
   303.5 1072.24   309.3 1071.38   318.4 1072.38   327.3 1073.87   336.3  1073.9
   383.8 1074.24   416.9 1075.22   485.4 1075.48     498 1076.93   518.8  1077.9
   531.3 1077.22   556.2 1076.88   589.4 1077.25   601.8 1076.34   614.4 1076.51
#Mann= 6 ,-1,0
       0      .1       0   303.5    .045       0   318.4      .1       0
   336.3     .06       0  441.31     .07       0  481.31     .06       0
#XS Ineff= 2 , 0
                           440.2         1084.55
Permanent Ineff=
       F       F
Bank Sta=303.5,318.4
XS Rating Curve= 0 ,0
Exp/Cntr(USF)=0,0
Exp/Cntr=0.3,0.1

Type RM Length L Ch R = 1 ,6521    ,43.4,42.2,43.5
BEGIN DESCRIPTION:
Structure 5 XS 3
END DESCRIPTION:
XS GIS Cut Line= 6
1705448.10709276437881.3635822281705222.90244347438066.549286868
1705204.85468412438043.7934163831705178.96007288438028.884397789
1705120.10868369438019.4681755191704941.20046057438171.697102215
#Sta/Elev= 30
       0 1153.56    31.1  1138.7    49.1 1131.42    76.1  1116.4   101.7 1107.23
   118.4 1099.64   134.6  1088.1   147.2 1081.58   160.5 1078.84   169.9 1075.23
   181.3 1073.66   193.9 1073.88     241 1070.84   297.8 1071.15   335.2 1070.07
   344.5 1069.17   357.4 1066.13   368.5 1065.56   374.8 1066.19   389.9 1069.27
   406.1 1070.74   425.1  1070.9   436.4 1069.59   442.1 1073.74   446.9 1080.08
   450.6 1083.53   473.1 1098.41   536.2  1117.9   609.5 1154.75     645 1168.39
#Mann= 5 ,-1,0
       0      .1       0     200     .06       0   357.4    .045       0
   374.8     .06       0  510.11      .1       0
Bank Sta=357.4,374.8
XS Rating Curve= 0 ,0
Exp/Cntr(USF)=0,0
Exp/Cntr=0.3,0.1

Type RM Length L Ch R = 1 ,6478    ,482.4,478.3,470.1
BEGIN DESCRIPTION:
Structure 5 XS 2
END DESCRIPTION:
XS GIS Cut Line= 6
1705437.29692602437861.4311533021705238.59614726438029.669082978
1705211.91685082438005.3438421151705168.75916542437992.004193899
1705083.19432237437977.872606351  1704900.750189438148.857185119
#Sta/Elev= 30
       0 1156.76    29.6 1142.11    48.7 1135.17    82.5 1116.95     110 1106.68
   128.6 1095.46   137.8 1091.25     145 1086.46     162 1079.21   171.9 1075.95
     185  1073.6   227.7 1070.17   332.1 1070.05   346.3 1069.06   359.9 1066.09
   370.1 1065.29   379.1 1066.04   411.2 1069.75   438.2 1070.69     458 1069.64
   469.3  1072.7   473.3 1074.53   479.2 1079.05   490.9 1089.55   506.1 1099.36
   559.9 1117.98   608.1 1142.13   635.5 1154.12   648.8 1158.84   678.5 1166.88
#Mann= 6 ,-1,0
       0      .1       0     230     .06       0  306.46      .1       0
   359.9    .045       0   379.1     .06       0  478.49      .1       0
Bank Sta=359.9,379.1
XS Rating Curve= 0 ,0
Exp/Cntr(USF)=0,0
Exp/Cntr=0.3,0.1

Type RM Length L Ch R = 1 ,6000    ,504.6,500,494.8
BEGIN DESCRIPTION:
Structure 5 XS 1
END DESCRIPTION:
XS GIS Cut Line= 6
 1705171.1075701437421.1851668361704953.80747975437556.996575013
 1704869.0077806437609.9971251791704805.40784217437649.746717587
1704734.49787901437701.3853938431704662.04920501437762.323264092
#Sta/Elev= 30
       0 1187.72      29 1181.83    74.2 1169.95    91.7 1163.51     112  1153.4
   152.6 1141.13     195 1130.74   211.1 1122.48   242.6 1104.31   265.9 1094.39
   271.7  1089.4   291.3 1066.98     296 1063.83   310.1  1062.8   315.8 1063.67
   324.3 1066.36   373.3 1066.75   390.3 1069.37   457.6 1068.64   483.6 1069.03
   510.7 1070.93   532.5  1070.3   542.8 1072.49     557 1080.54   569.1 1084.26
   574.4 1087.65     586 1098.49   598.4 1105.32   604.7 1107.45   613.6 1108.64
#Mann= 4 ,-1,0
       0      .1       0     296    .045       0   315.8      .1       0
  376.25     .06       0
Bank Sta=296,315.8
XS Rating Curve= 0 ,0
Exp/Cntr(USF)=0,0
Exp/Cntr=0.3,0.1

Type RM Length L Ch R = 1 ,5500    ,120.6,120.5,120.3
BEGIN DESCRIPTION:
Structure 4 XS 4
END DESCRIPTION:
XS GIS Cut Line= 6
1704653.52789658437018.696798593 1704535.9060846 437246.35579209
1704489.93603218437335.1630291791704455.47251843437401.776413009
 1704415.2901841437479.5046040121704372.24860351437562.790854752
#Sta/Elev= 30
       0 1201.75    74.1 1168.06   105.6 1152.08     136 1140.14   153.8 1128.16
   162.7 1123.17   213.2  1110.1   225.1 1105.62   267.7 1078.69   276.7 1071.01
   290.4 1064.51   299.3 1059.25   299.3 1059.24     308  1058.1  313.361059.239
   321.8 1063.19   443.4 1064.08   461.4 1065.26   474.9 1067.52   501.1 1067.51
     513 1076.92   524.8 1080.37   533.4 1085.44   542.7 1093.84   551.4 1103.55
   555.9 1106.86   573.9 1114.95   587.5 1117.33     601 1123.98   612.5 1131.79
#Mann= 5 ,-1,0
       0      .1       0   299.3    .045       0  313.36      .1       0
  426.25     .06       0  451.25      .1       0
Bank Sta=299.3,313.36
XS Rating Curve= 0 ,0
Exp/Cntr(USF)=0,0
Exp/Cntr=0.3,0.1

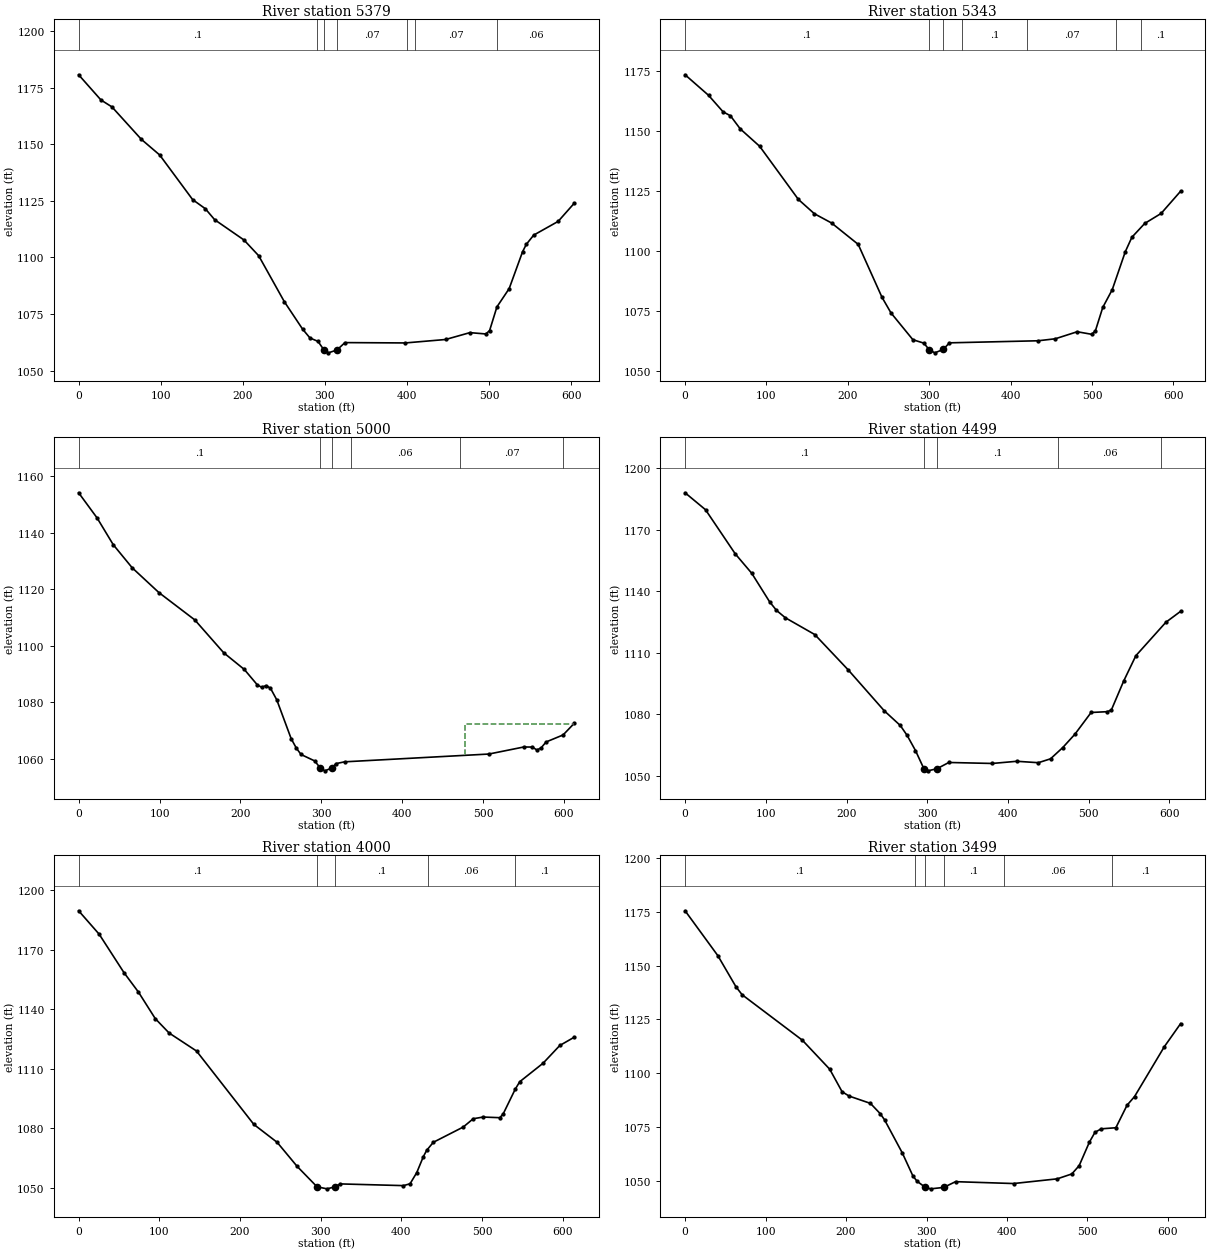
Type RM Length L Ch R = 1 ,5379    ,36.3,36.5,36.4
BEGIN DESCRIPTION:
Structure 4 XS 3
END DESCRIPTION:
XS GIS Cut Line= 2
1704542.58038448436960.1431701631704274.21804979437500.791265489
#Sta/Elev= 30
       0 1180.62    27.2 1169.49    40.6 1166.43    76.4 1152.12    98.7 1145.22
   138.9  1125.5   154.3  1121.5   165.7 1116.64   201.4 1107.69   219.3 1100.75
   250.5 1080.48   272.8 1068.34   281.8 1064.42   291.6 1062.93  298.78 1059.16
   304.1 1057.87   314.6 1059.11   324.4 1062.39   397.9 1062.24     447 1063.76
   476.6 1066.79   496.1  1066.2   500.6 1067.72   509.5 1078.15   524.4 1086.21
   540.8 1102.55   545.3 1105.76   554.3 1109.84   584.1  1115.9   603.6 1123.88
#Mann= 7 ,-1,0
       0      .1       0     290     .07       0  298.78    .045       0
   314.6     .07       0     400     .06       0     410     .07       0
     510     .06       0
Bank Sta=298.78,314.6
XS Rating Curve= 0 ,0
Exp/Cntr(USF)=0,0
Exp/Cntr=0.3,0.1

Type RM Length L Ch R = 1 ,5343    ,341.1,343,345.6
BEGIN DESCRIPTION:
Structure 4 XS 2
END DESCRIPTION:
XS GIS Cut Line= 2
1704513.54703248436942.8800960021704238.12253109437485.882246896
#Sta/Elev= 30
       0 1173.54    28.8 1164.99    46.7 1158.09    55.7 1156.46    67.8 1150.98
    91.6 1143.74   139.2 1121.59   158.8 1115.64     180 1111.76   212.7 1102.86
   241.9 1080.83     253 1074.29   279.9 1063.12   293.4 1061.69   299.9 1058.96
   306.8 1057.65   317.11059.049   324.8 1061.82   433.8 1062.68   454.9 1063.51
   481.8 1066.44   499.7 1065.37   504.2 1066.87   513.2 1076.57   524.9 1084.01
   540.9  1099.8     549 1105.83   564.8 1111.59   584.9 1115.74   608.9 1125.02
#Mann= 7 ,-1,0
       0      .1       0   299.9    .045       0   317.1     .07       0
     340      .1       0     420     .07       0     530     .06       0
     560      .1       0
Bank Sta=299.9,317.1
XS Rating Curve= 0 ,0
Exp/Cntr(USF)=0,0
Exp/Cntr=0.3,0.1

Type RM Length L Ch R = 1 ,5000    ,498.6,500.5,501.1
BEGIN DESCRIPTION:
Structure 4 XS 1
END DESCRIPTION:
XS GIS Cut Line= 6
1704312.54235809436776.8140802531704249.58743151436846.281789094
1704190.83065926436911.1192578381704073.31580243437040.792883009
1704022.95172992437096.3669188321703901.23970301437230.671768337
#Sta/Elev= 30
       0 1154.12    22.8 1145.23    42.8 1135.76    66.2  1127.6    99.2 1118.84
   143.6 1109.17   179.3 1097.56   204.8 1091.65     221 1086.16   226.3 1085.34
   231.7 1085.96   237.1 1085.03   244.9 1080.92   262.7 1067.18   269.1 1063.84
   274.9 1061.59   291.8 1059.31   298.5 1056.89   304.4 1055.81  313.371056.883
   318.1 1058.37   328.9    1059   507.1 1061.75   550.2 1064.24   560.8 1064.22
   566.5 1063.16   571.8 1063.99   577.8 1066.02   598.8  1068.5   612.5 1072.58
#Mann= 6 ,-1,0
       0      .1       0   298.5    .045       0  313.37      .1       0
  336.25     .06       0  471.25     .07       0  598.75      .1       0
#XS Ineff= 2 , 0
                          477.97         1072.48
Permanent Ineff=
       F       F
Bank Sta=298.5,313.37
XS Rating Curve= 0 ,0
Exp/Cntr(USF)=0,0
Exp/Cntr=0.3,0.1

Type RM Length L Ch R = 1 ,4499    ,493.7,499.5,503.6
XS GIS Cut Line= 6
1704027.54391234 436428.465695591703830.68439792436592.509986922
 1703753.1750385436655.7267239991703692.81393875436700.972368419
1703622.80325201436754.2685216671703548.09900509436811.664732337
#Sta/Elev= 30
       0 1187.95    25.3 1179.68    62.1 1158.18    82.6 1148.66   104.7 1134.77
   113.2 1130.59   124.2 1126.98   160.7 1118.78   202.3 1101.46   246.7 1081.62
   266.6 1074.43   275.1 1069.57   285.4 1062.22   295.7 1053.45   300.7 1052.31
   312.1 1053.35   326.7 1056.39   380.5 1055.91     411 1056.97   437.6 1056.28
   452.7 1058.17   467.8 1063.64   482.9 1070.17     503 1080.78   523.2 1081.17
   528.1 1082.02   543.2    1096   558.4 1108.46   595.6 1124.78   613.9 1130.13
#Mann= 5 ,-1,0
       0      .1       0   295.7    .045       0   312.1      .1       0
  461.71     .06       0   589.7      .1       0
Bank Sta=295.7,312.1
XS Rating Curve= 0 ,0
Exp/Cntr(USF)=0,0
Exp/Cntr=0.3,0.1

Type RM Length L Ch R = 1 ,4000    ,508.9,500.6,488.5
XS GIS Cut Line= 6
1703787.28192568436130.0821060091703700.18826784436168.004274249
1703617.41284284436197.7857107521703544.57210925436215.652144834
1703289.62872151436278.183187753 1703198.5777225436300.516148344
#Sta/Elev= 30
       0 1189.51    25.5  1177.7    56.2 1158.38    74.2 1148.56      95 1135.23
   112.1 1128.01   146.1 1118.94   217.2 1081.98   246.1 1072.96   270.8 1060.89
   295.5 1050.59   307.9 1049.57  317.811050.584   324.3 1052.05   402.6 1051.19
   410.8 1052.12   419.1 1057.75   427.3 1065.82   431.4 1068.95   439.6 1072.99
   476.7 1080.67   489.1 1084.85   501.4  1085.7     522 1085.38   526.1 1087.18
   541.1 1099.68   546.7 1103.47   575.6 1112.77   596.4 1121.72   614.2 1125.86
#Mann= 5 ,-1,0
       0      .1       0   295.5    .045       0  317.81      .1       0
  432.96     .06       0  540.46      .1       0
Bank Sta=295.5,317.81
XS Rating Curve= 0 ,0
Exp/Cntr(USF)=0,0
Exp/Cntr=0.3,0.1

Type RM Length L Ch R = 1 ,3499    ,494.1,497.6,503.3
XS GIS Cut Line= 6
1703312.42263918435582.9224391731703206.38512158435816.203796759
 1703164.0033166435906.7849804161703128.33311234435973.218246505
1703087.07728934 436051.556344421703038.59739943436133.966284588
#Sta/Elev= 30
       0 1175.43    40.7  1154.6    63.3 1140.11    70.9 1136.46   145.7 1115.38
   179.7 1101.92   195.1 1091.46   203.8 1089.45   230.3 1086.06   242.4 1081.31
   247.8 1078.47   269.9 1063.07   283.1 1052.38   288.3  1049.9  298.481047.097
   305.2  1046.4   321.4 1047.06   336.1 1049.73   408.2 1048.86   462.5 1051.04
   480.6 1053.32   489.7 1057.16   502.4 1068.06   509.4 1072.66   517.2 1074.25
   535.3 1074.75   549.2  1085.2   558.5 1089.21   595.6  1112.4   615.8 1123.08
#Mann= 6 ,-1,0
       0      .1       0  286.25     .05       0  298.48    .045       0
   321.4      .1       0  396.26     .06       0   530.2      .1       0
Bank Sta=298.48,321.4
XS Rating Curve= 0 ,0
Exp/Cntr(USF)=0,0
Exp/Cntr=0.3,0.1

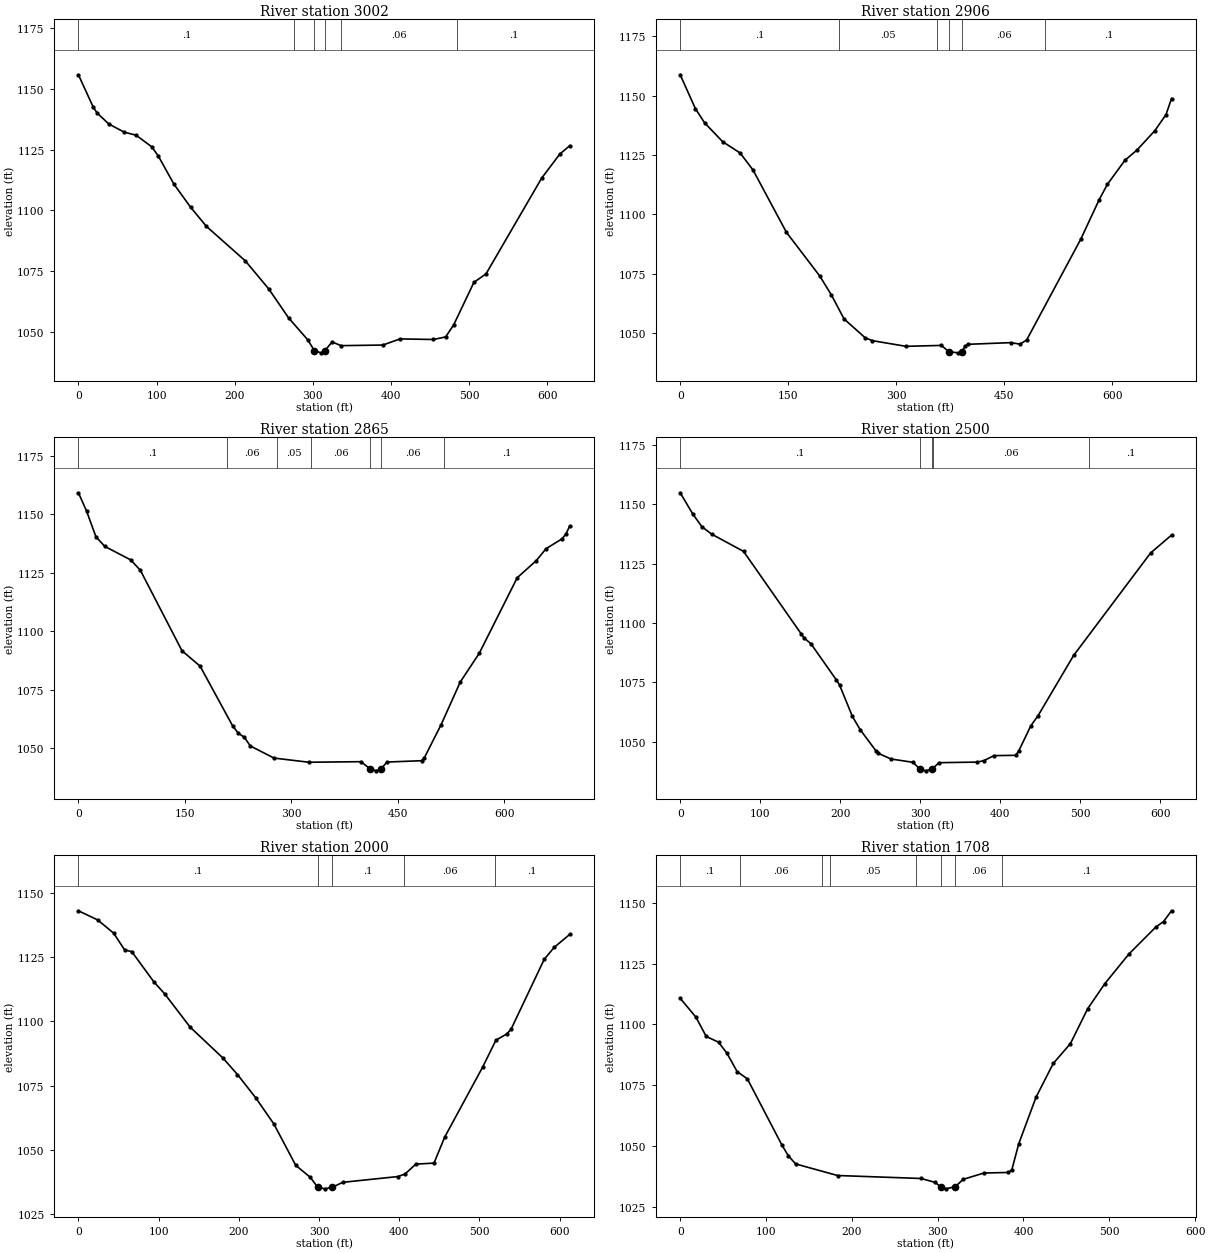
Type RM Length L Ch R = 1 ,3002    ,97.7,96,92.3
BEGIN DESCRIPTION:
Structure 3 XS 4
END DESCRIPTION:
XS GIS Cut Line= 6
1703099.13402376435344.4455539291702894.13607417435498.198199168
1702816.28911701435561.247285679  1702759.084507435615.356429428
1702686.69718459435674.8064417541702607.82365467435736.317801669
#Sta/Elev= 30
       0  1155.7    18.8 1142.53    23.8 1140.07    38.8 1135.51    58.8 1132.12
    73.8  1130.9    93.8 1126.15   102.2 1122.38   122.2 1110.83   143.8 1101.24
   163.8 1093.49   213.7 1079.29   243.8 1067.72   269.1 1055.87   293.5 1046.92
     302 1042.51   310.3 1041.55   315.5 1042.46   324.8 1046.03   336.1  1044.5
   389.7 1044.75   411.7 1047.27   454.5 1047.03   470.1 1048.09   480.4 1053.05
   506.3  1070.5   521.8 1073.98     593 1113.28   616.2 1123.14   628.9 1126.57
#Mann= 6 ,-1,0
       0      .1       0  276.25     .05       0     302    .045       0
   315.5     .05       0  336.25     .06       0  485.17      .1       0
Bank Sta=302,315.5
XS Rating Curve= 0 ,0
Exp/Cntr(USF)=0,0
Exp/Cntr=0.3,0.1

Type RM Length L Ch R = 1 ,2906    ,40.7,41.1,40.9
BEGIN DESCRIPTION:
Structure 3 XS 3
END DESCRIPTION:
XS GIS Cut Line= 4
1703092.18899418435307.5767832221702819.58935947435397.266300342
1702747.55525911435528.622601006  1702529.334308435640.911051574
#Sta/Elev= 30
       0 1158.84    21.1 1144.55    33.8  1138.6      59  1130.6    83.2 1125.86
   101.1 1118.67   147.5 1092.39   193.8 1073.94   209.9 1065.98   227.5 1055.85
   256.9 1047.89     267 1046.68   313.5  1044.3   362.7 1044.68   372.8 1042.09
   385.7 1041.55   391.1 1042.07   395.6 1044.36   400.2 1045.16   458.7 1045.85
   472.1 1045.22   481.1    1047   556.2 1089.48   581.8 1106.18   593.2 1112.63
   617.5 1122.77   634.1 1127.04   659.1 1135.28   674.6 1142.06   682.2  1148.8
#Mann= 6 ,-1,0
       0      .1       0     220     .05       0  356.98     .06       0
   372.8    .045       0   391.1     .06       0  506.79      .1       0
Bank Sta=372.8,391.1
XS Rating Curve= 0 ,0
Exp/Cntr(USF)=0,0
Exp/Cntr=0.3,0.1

Type RM Length L Ch R = 1 ,2865    ,360.1,364.7,374.7
BEGIN DESCRIPTION:
Structure 3 XS 2
END DESCRIPTION:
XS GIS Cut Line= 4
1703083.71439414435265.9099996781702798.40285936435353.480866788
 1702707.3009089435516.616917612 1702522.2721413435609.837518084
#Sta/Elev= 30
       0 1159.16    11.4 1151.41    24.7 1140.37    37.2 1136.26    73.9 1130.46
    87.4 1126.01     146 1091.69   171.5 1085.13   217.2 1059.72   225.5 1056.44
   233.9 1054.77   242.3 1051.05   275.7 1045.87   324.9 1044.09   398.2 1044.33
   411.1 1041.27     420 1040.42  426.751041.277   434.8 1044.17   483.6 1044.75
   487.6 1046.01   511.3 1060.17   538.2 1078.33   565.1 1090.68   618.5 1122.88
   645.5 1130.23   659.1 1135.27   681.5 1139.47   687.2 1141.53   692.5 1144.98
#Mann= 7 ,-1,0
       0      .1       0     210     .06       0     280     .05       0
  328.45     .06       0   411.1    .045       0  426.75     .06       0
   515.3      .1       0
Bank Sta=411.1,426.75
XS Rating Curve= 0 ,0
Exp/Cntr(USF)=0,0
Exp/Cntr=0.3,0.1

Type RM Length L Ch R = 1 ,2500    ,503,500,495.6
BEGIN DESCRIPTION:
Structure 3 XS 1
END DESCRIPTION:
XS GIS Cut Line= 6
1702999.28448592435087.1914752571702905.58093317435090.150786921
1702643.21203534435098.4358753411702568.24925876435100.804965094
1702480.82358059435110.9145249281702387.01110417435125.193367749
#Sta/Elev= 30
       0 1154.83      16 1145.74    27.2 1140.54    39.3 1137.42    79.2 1130.16
   151.2 1095.48   155.2 1093.63   163.3 1091.35   195.3 1076.03   199.3 1073.85
   215.3 1060.68     225 1055.14   244.9 1046.14   247.3 1045.25   263.3 1042.81
   291.3 1041.38   299.3 1038.59     307 1037.81   315.3 1038.62   323.3 1041.24
   371.4 1041.49   379.4 1042.08   392.3 1044.21   419.4 1044.34   423.4 1046.31
   438.3 1056.75   447.5 1061.09   491.8 1086.36     588 1129.47   614.2 1137.01
#Mann= 5 ,-1,0
       0      .1       0   299.3    .045       0   315.3      .1       0
  316.25     .06       0  511.25      .1       0
Bank Sta=299.3,315.3
XS Rating Curve= 0 ,0
Exp/Cntr(USF)=0,0
Exp/Cntr=0.3,0.1

Type RM Length L Ch R = 1 ,2000    ,289.8,292.3,294.9
XS GIS Cut Line= 6
1702750.91588818434505.2090434281702668.27694584434549.479952261
  1702591.147835434590.7994234261702525.03674676434626.216019258
1702370.77754085 434708.854633511702211.00915959434794.444357336
#Sta/Elev= 30
       0 1143.11      24 1139.54      44 1134.37    57.6 1127.87    66.6 1127.16
    93.9 1115.48   107.5 1110.76   139.3 1097.77   180.2 1085.72   198.3  1079.3
     221 1070.24   243.7 1060.01   270.9 1043.93   289.1 1039.23   298.1 1035.45
   307.2 1034.75   316.3 1035.34   329.6 1037.29     398 1039.53     407 1040.48
   420.7 1044.39   443.3 1044.77   456.6 1054.88   503.9 1082.16   520.5 1092.67
   534.1 1095.12   539.4 1096.96   580.7 1124.18   593.1 1128.84   612.5 1133.89
#Mann= 5 ,-1,0
       0      .1       0   298.1    .045       0   316.3      .1       0
  406.25     .06       0  518.75      .1       0
Bank Sta=298.1,316.3
XS Rating Curve= 0 ,0
Exp/Cntr(USF)=0,0
Exp/Cntr=0.3,0.1

Type RM Length L Ch R = 1 ,1708    ,46.7,46.8,46.5
XS GIS Cut Line= 4
1702658.43161039434360.0390693141702533.74739359434356.757905713
1702279.45721459434402.6941961141702090.79030758434386.288378114
#Sta/Elev= 30
       0 1110.71    18.3 1102.96    30.3 1095.04    44.7 1092.63    54.3  1088.2
    66.3 1080.58    78.3 1077.53   118.4 1050.38   125.9 1045.94   134.5 1042.53
   183.3 1037.77   280.8 1036.54   297.1 1034.93  303.411033.118   309.3 1032.28
   320.5 1033.14   329.6 1036.17     354  1038.8   382.5 1039.02   386.5 1040.21
   394.5 1050.84   414.6 1069.98   434.7  1083.9   454.7 1092.06   474.8 1106.42
   494.9  1116.8     523    1129   554.4 1140.11   563.2  1142.3   572.5 1146.75
#Mann= 8 ,-1,0
       0      .1       0      70     .06       0  164.73      .1       0
  174.73     .05       0  274.73     .06       0  303.41    .045       0
   320.5     .06       0  374.73      .1       0
Bank Sta=303.41,320.5
XS Rating Curve= 0 ,0
Exp/Cntr(USF)=0,0
Exp/Cntr=0.3,0.1