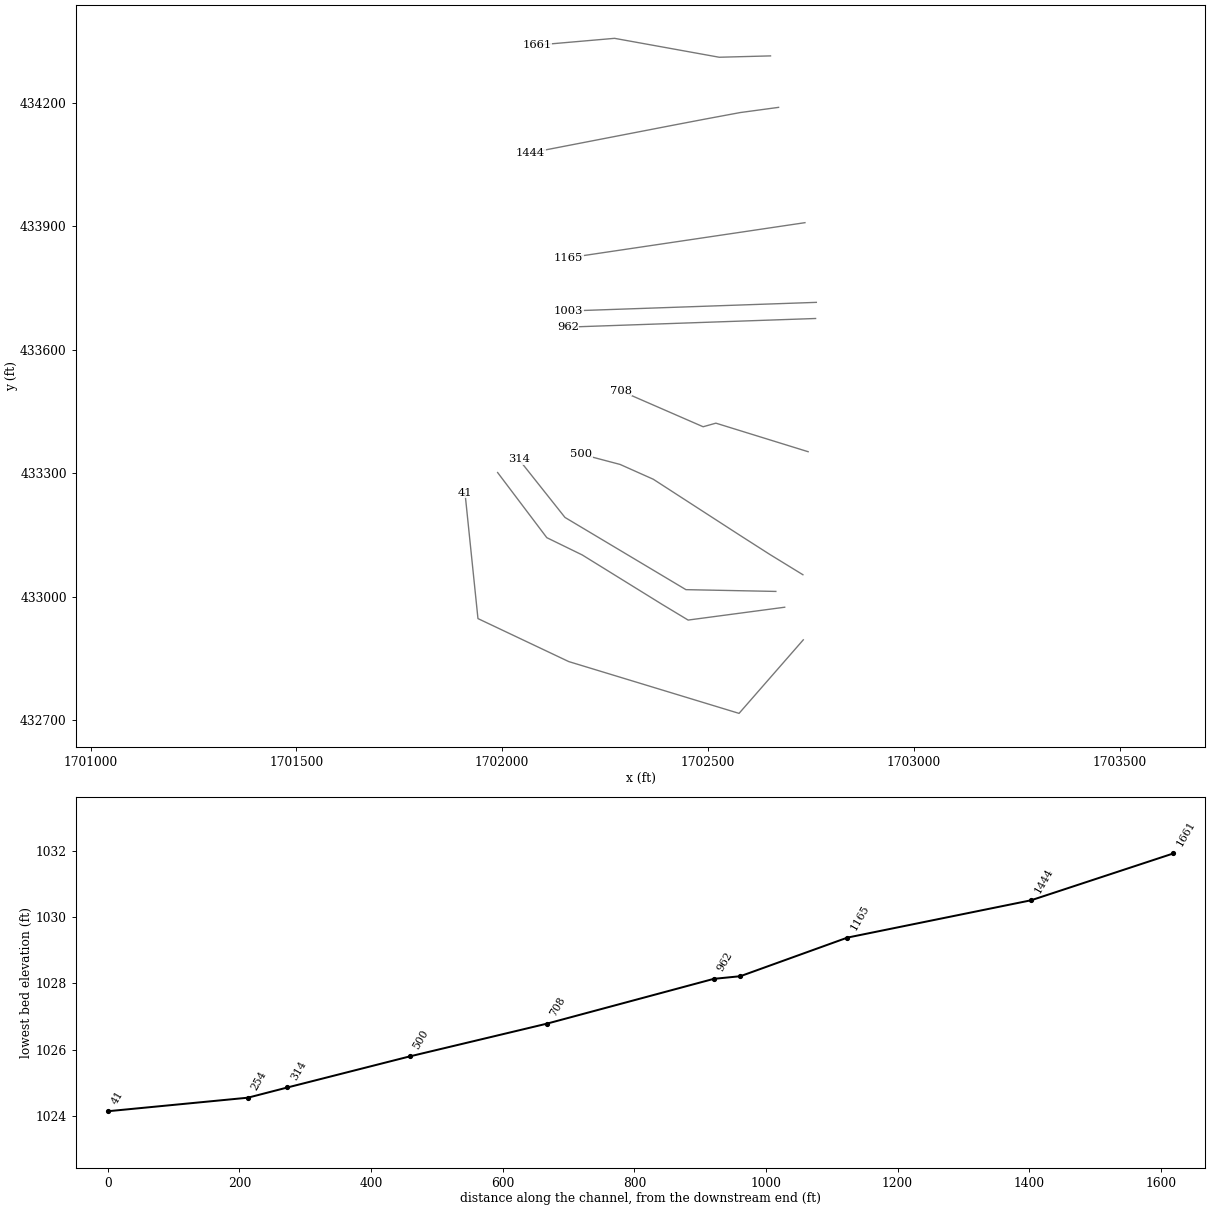
HEC-RAS study CAPPORN.prj: CAPPORN

--- CAPPORN.g01 (geometry) --- (continued)

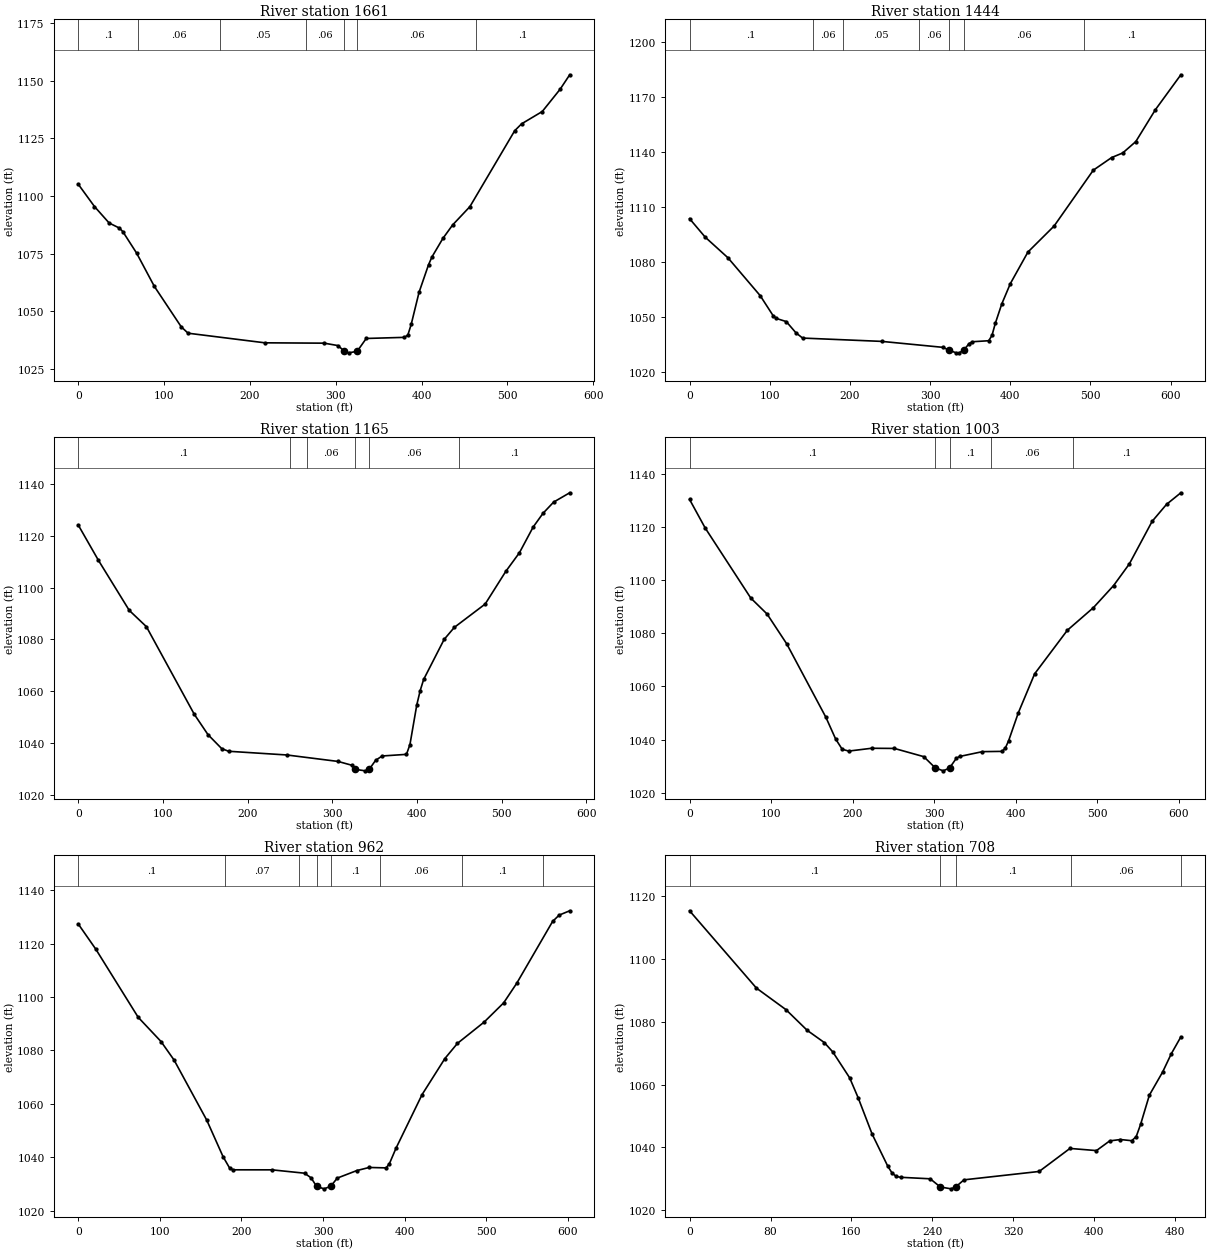
Type RM Length L Ch R = 1 ,1661    ,213.2,216.4,219.3
XS GIS Cut Line= 4
1702651.86928319434314.1027789131702527.18506639434310.821615313
1702272.89488739434356.7579057141702084.22798038434340.352087713
#Sta/Elev= 30
       0 1105.03    18.7 1095.46    35.8  1088.3    47.8 1086.09    51.8 1084.53
    67.8 1075.24    88.5 1060.77   119.8 1043.24   127.8 1040.46   217.3 1036.29
   286.4 1036.14   302.6 1035.08     310 1032.57   314.8 1031.94   324.8 1032.59
   335.4 1038.18   379.9 1038.66   383.9 1039.68   387.8 1044.31   396.9 1058.18
     408 1070.19     412 1073.59   424.7  1081.6   436.1 1087.47   456.2 1095.41
   508.4 1128.36   516.4 1131.34   540.5 1136.69   561.4  1146.4   572.5 1152.64
#Mann= 7 ,-1,0
       0      .1       0      70     .06       0  164.73     .05       0
  264.73     .06       0     310    .045       0   324.8     .06       0
  463.13      .1       0
Bank Sta=310,324.8
XS Rating Curve= 0 ,0
Exp/Cntr(USF)=0,0
Exp/Cntr=0.3,0.1

Type RM Length L Ch R = 1 ,1444    ,279.3,279,278.6
XS GIS Cut Line= 6
1702671.45855908434189.0459290891702578.40592366434176.453762666
1702492.37919282434160.4528104221702418.71136116434146.378691584
1702320.53307983434127.3767610941702068.95189008434078.683617011
#Sta/Elev= 30
       0 1103.66    19.5 1093.59    47.8 1082.37    88.1 1061.69   104.4 1050.66
   108.4 1049.25   120.6 1047.56   132.8 1041.38     141 1038.57   239.7 1036.76
   316.1 1033.51     323 1032.09   332.4 1030.52   336.5 1030.53   342.1 1032.09
   348.7  1035.6   352.8 1036.57   373.1 1037.12   377.2 1040.07   381.3 1046.59
   389.4 1057.21   400.1 1068.29     422 1085.47   454.6 1099.63   503.5 1130.08
   526.4 1136.97   540.2 1139.47   556.5 1145.67   580.9 1163.02   612.7 1182.09
#Mann= 7 ,-1,0
       0      .1       0   153.9     .06       0   191.4     .05       0
   286.4     .06       0     323    .045       0   342.1     .06       0
   491.4      .1       0
Bank Sta=323,342.1
XS Rating Curve= 0 ,0
Exp/Cntr(USF)=0,0
Exp/Cntr=0.3,0.1

Type RM Length L Ch R = 1 ,1165    ,164.3,162.8,162.2
BEGIN DESCRIPTION:
Structure 2 XS 4
END DESCRIPTION:
XS GIS Cut Line= 2
  1702735.538955433908.8790743041702161.33532498433823.568820703
#Sta/Elev= 30
       0 1123.95    23.7 1110.44    60.1 1091.18    80.3 1084.93   136.9 1051.17
   153.1 1043.33   169.3 1037.95   177.4 1036.93   246.3  1035.5   306.8 1033.01
   322.9 1031.56     327 1029.96   339.1 1029.39  343.641030.001   351.2 1033.46
   358.9 1035.11   387.6 1035.74   391.7 1039.47   399.8 1054.78   403.8 1060.26
   407.9 1064.58   432.1    1080   444.2 1084.65   480.6 1093.63   504.9 1106.18
   521.1  1113.4   537.3 1123.29     549  1128.6   561.5  1132.9   580.5 1136.49
#Mann= 6 ,-1,0
       0      .1       0     250     .05       0     270     .06       0
     327    .045       0  343.64     .06       0     450      .1       0
Bank Sta=327,343.64
XS Rating Curve= 0 ,0
Exp/Cntr(USF)=0,0
Exp/Cntr=0.3,0.1

Type RM Length L Ch R = 1 ,1003    ,39.6,40.4,39.7
BEGIN DESCRIPTION:
Structure 2 XS 3
END DESCRIPTION:
XS GIS Cut Line= 2
1702763.19823957433715.2773940011702160.94405129433694.318770229
#Sta/Elev= 30
       0 1130.44    19.1 1119.72    75.1 1093.29    95.1 1087.28   119.2 1076.04
   167.2  1048.4   179.2  1040.2   187.2 1036.35   195.2 1035.66   223.2 1036.72
   251.2 1036.66   287.3 1033.56  301.341029.338   311.2 1028.22   318.9 1029.31
   327.3 1032.98   331.3 1033.64   359.3 1035.45   383.3 1035.55   387.3 1036.79
   391.3 1039.52   403.3 1050.12   423.3 1064.78   463.4 1081.17   495.4  1089.7
   520.1    1098   539.4 1106.15   567.4  1122.2     585 1128.58   602.6 1132.95
#Mann= 5 ,-1,0
       0      .1       0  301.34    .045       0   318.9      .1       0
     370     .06       0     470      .1       0
Bank Sta=301.34,318.9
XS Rating Curve= 0 ,0
Exp/Cntr(USF)=0,0
Exp/Cntr=0.3,0.1

Type RM Length L Ch R = 1 ,962     ,252.4,254.1,256.3
BEGIN DESCRIPTION:
Structure 2 XS 2
END DESCRIPTION:
XS GIS Cut Line= 2
1702761.38051595 433676.082230851702159.12632768433655.123607078
#Sta/Elev= 30
       0  1127.3    21.3 1117.96    73.3 1092.43   101.3 1083.35   117.3 1076.42
   157.4 1053.89   177.4  1040.2   185.4 1035.96   189.4 1035.27   237.4 1035.26
   277.4    1034   285.4 1032.26   292.1 1029.06   301.4 1028.14   309.5 1029.11
   317.5 1032.17   341.5 1034.99   356.6 1036.15   377.5 1035.99   381.5 1037.61
   389.5 1043.34   421.5 1063.45   449.5 1076.97   464.9 1082.65   497.6 1090.62
   521.6 1097.84   537.6 1105.17   581.6 1128.33   589.6 1130.71   602.6 1132.34
#Mann= 8 ,-1,0
       0      .1       0     180     .07       0     270      .1       0
   292.1    .045       0   309.5      .1       0     370     .06       0
     470      .1       0     570     .06       0
Bank Sta=292.1,309.5
XS Rating Curve= 0 ,0
Exp/Cntr(USF)=0,0
Exp/Cntr=0.3,0.1

Type RM Length L Ch R = 1 ,708     ,214.9,208.1,202.1
BEGIN DESCRIPTION:
Structure 2 XS 1
END DESCRIPTION:
XS GIS Cut Line= 4
1702743.25867985433352.4098054351702519.15568173433421.771930547
1702488.15577302433413.0532062231702287.66012359433500.374206096
#Sta/Elev= 30
       0 1115.41    66.1 1090.76    95.3 1083.89   116.3 1077.29   133.1 1073.42
   141.5 1070.44   158.2 1062.17   166.6 1055.82   180.4 1044.24   195.9 1033.98
   200.1 1031.83   204.3 1030.73   208.5 1030.46   237.8 1029.98   247.8 1027.37
   258.5 1026.78  262.941027.382   271.2 1029.65   345.5 1032.32   375.9 1039.66
   402.1 1038.97   415.2 1042.06   425.8  1042.5     437 1042.12   441.4 1043.44
   445.7  1047.3   454.4 1056.65   467.5 1064.02   476.1 1069.86   485.5 1075.21
#Mann= 5 ,-1,0
       0      .1       0   247.8    .045       0  262.94      .1       0
  376.79     .06       0  485.48      .1       0
Bank Sta=247.8,262.94
XS Rating Curve= 0 ,0
Exp/Cntr(USF)=0,0
Exp/Cntr=0.3,0.1

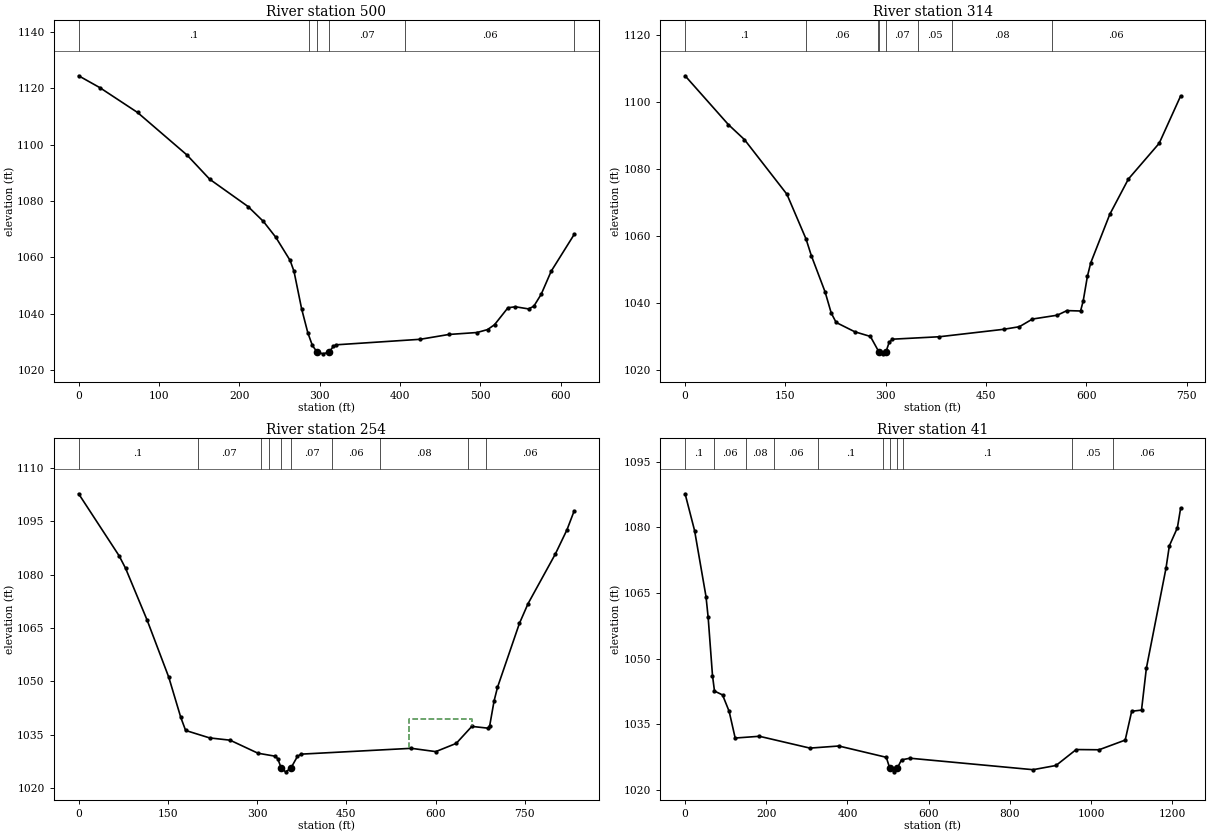
Type RM Length L Ch R = 1 ,500     ,185.2,185.6,185.7
BEGIN DESCRIPTION:
Structure 1 XS 4
END DESCRIPTION:
XS GIS Cut Line= 6
1702730.56619135433053.4970518351702650.62507826 433102.52385667
1702576.92903142 433149.696662591702367.03640659433285.509711176
1702286.35185668433321.491594583  1702192.479341433346.274681509
#Sta/Elev= 30
       0 1124.38    26.3 1120.19    73.3 1111.37   134.8  1096.3   163.2 1087.68
   210.8 1078.03   229.9 1072.75   245.4 1067.11   263.2  1058.9     268 1055.08
   277.5 1041.78   285.2 1033.29   290.9 1028.76   296.7 1026.46   304.3 1025.79
   311.7 1026.45     317 1028.41   320.4 1028.99   425.2 1030.95   460.8 1032.66
   495.8 1033.35   508.9 1034.39   517.6 1036.12   534.3 1042.13   543.6 1042.48
   559.9 1041.72   566.5 1042.67   575.7 1046.93   588.1 1055.08   616.7 1068.12
#Mann= 6 ,-1,0
       0      .1       0  286.28     .07       0   296.7    .045       0
   311.7     .07       0  406.28     .06       0  616.71      .1       0
Bank Sta=296.7,311.7
XS Rating Curve= 0 ,0
Exp/Cntr(USF)=0,0
Exp/Cntr=0.3,0.1

Type RM Length L Ch R = 1 ,314     ,60.4,60.2,59.4
BEGIN DESCRIPTION:
Structure 1 XS 3
END DESCRIPTION:
XS GIS Cut Line= 4
1702664.82003365433012.964624484 1702446.3137327 433017.27016736
1702152.46043141433192.7210395571702040.51631663433333.727568746
#Sta/Elev= 30
       0  1107.8    64.7 1093.24    88.7 1088.77   152.2 1072.46   180.8 1059.11
   188.7 1054.16   209.3 1043.31   218.5    1037   225.8 1034.21   253.7 1031.43
     277 1030.04   289.6 1025.48   295.5 1024.85   300.3 1025.47     305 1028.25
     310 1029.22   380.1 1029.95   476.3 1032.17   499.7 1032.94   519.3 1035.23
   556.5 1036.38   570.8 1037.75   591.2 1037.63   595.1 1040.59   601.4 1047.96
   606.4 1051.99   634.9 1066.48   662.7    1077   708.7 1087.65   740.8 1101.78
#Mann= 8 ,-1,0
       0      .1       0     180     .06       0  288.55     .07       0
   289.6    .045       0   300.3     .07       0  348.55     .05       0
  398.55     .08       0  548.55     .06       0
Bank Sta=289.6,300.3
XS Rating Curve= 0 ,0
Exp/Cntr(USF)=0,0
Exp/Cntr=0.3,0.1

Type RM Length L Ch R = 1 ,254     ,212,212.7,215.8
BEGIN DESCRIPTION:
Structure 1 XS 2
END DESCRIPTION:
XS GIS Cut Line= 6
 1702686.3272967432974.5764042011702451.67520995 432943.36121835
1702389.24483825432981.0347185151702194.41902311433101.589919043
1702108.30816559433143.5689620841701988.82935078433301.797662777
#Sta/Elev= 30
       0  1102.8    67.9 1085.38    78.9 1081.82   115.2  1067.2   151.5 1051.16
   171.7 1039.85   179.8 1036.19   220.1 1034.09   254.5 1033.45   301.4 1029.78
   330.4 1028.94   334.6 1028.23   340.5 1025.62   347.8 1024.54   356.5 1025.53
   367.7 1028.88   373.9 1029.52   559.1 1031.16   600.2 1030.23   634.6 1032.55
   660.8 1037.33     688 1036.83   690.9 1037.58   698.2 1044.49   703.9  1048.3
   740.8 1066.33   755.3 1071.88   801.2 1085.86   820.7 1092.66   832.8 1097.98
#Mann= 10 ,-1,0
       0      .1       0     200     .07       0  306.72      .1       0
  319.64     .07       0   340.5    .045       0   356.5     .07       0
  426.55     .06       0  506.55     .08       0  654.55     .07       0
  684.55     .06       0
#XS Ineff= 1 ,-1
  555.72  660.68 1039.48
Permanent Ineff=
       T
Bank Sta=340.5,356.5
XS Rating Curve= 0 ,0
Exp/Cntr(USF)=0,0
Exp/Cntr=0.3,0.1

Type RM Length L Ch R = 1 ,41      ,,,
BEGIN DESCRIPTION:
Structure 1 XS 1
END DESCRIPTION:
XS GIS Cut Line= 5
1702731.47629569432895.3436514261702575.40036643432716.663622072
1702161.63769604432842.4931126231701941.06234138432946.971238668
1701909.54816065 433252.48843299
#Sta/Elev= 30
       0 1087.63    23.4 1079.21    51.5 1064.16    56.8 1059.42    67.5 1046.11
    72.4 1042.58    92.3 1041.69   108.5 1037.95   123.4 1031.85     183 1032.25
   307.6 1029.55   378.7 1030.03   495.7 1027.45   504.1    1025   515.5 1024.13
  522.75 1024.99   533.3 1026.87   554.2 1027.24   857.3 1024.62   913.8 1025.58
   963.6 1029.22  1019.9 1029.17  1084.3 1031.38  1100.3 1037.96  1124.5 1038.23
  1136.5 1047.81  1184.8 1070.62  1193.1 1075.75  1212.9 1079.87  1220.9 1084.37
#Mann= 11 ,-1,0
       0      .1       0      70     .06       0     150     .08       0
     220     .06       0  327.25      .1       0  487.25     .06       0
   504.1    .045       0  522.75     .06       0  537.25      .1       0
  953.79     .05       0 1053.79     .06       0
Bank Sta=504.1,522.75
XS Rating Curve= 0 ,0
Exp/Cntr(USF)=0,0
Exp/Cntr=0.3,0.1
LCMann Table=0

Chan Stop Cuts=-1
Use User Specified Reach Order=0
Composite Channel Slope=5